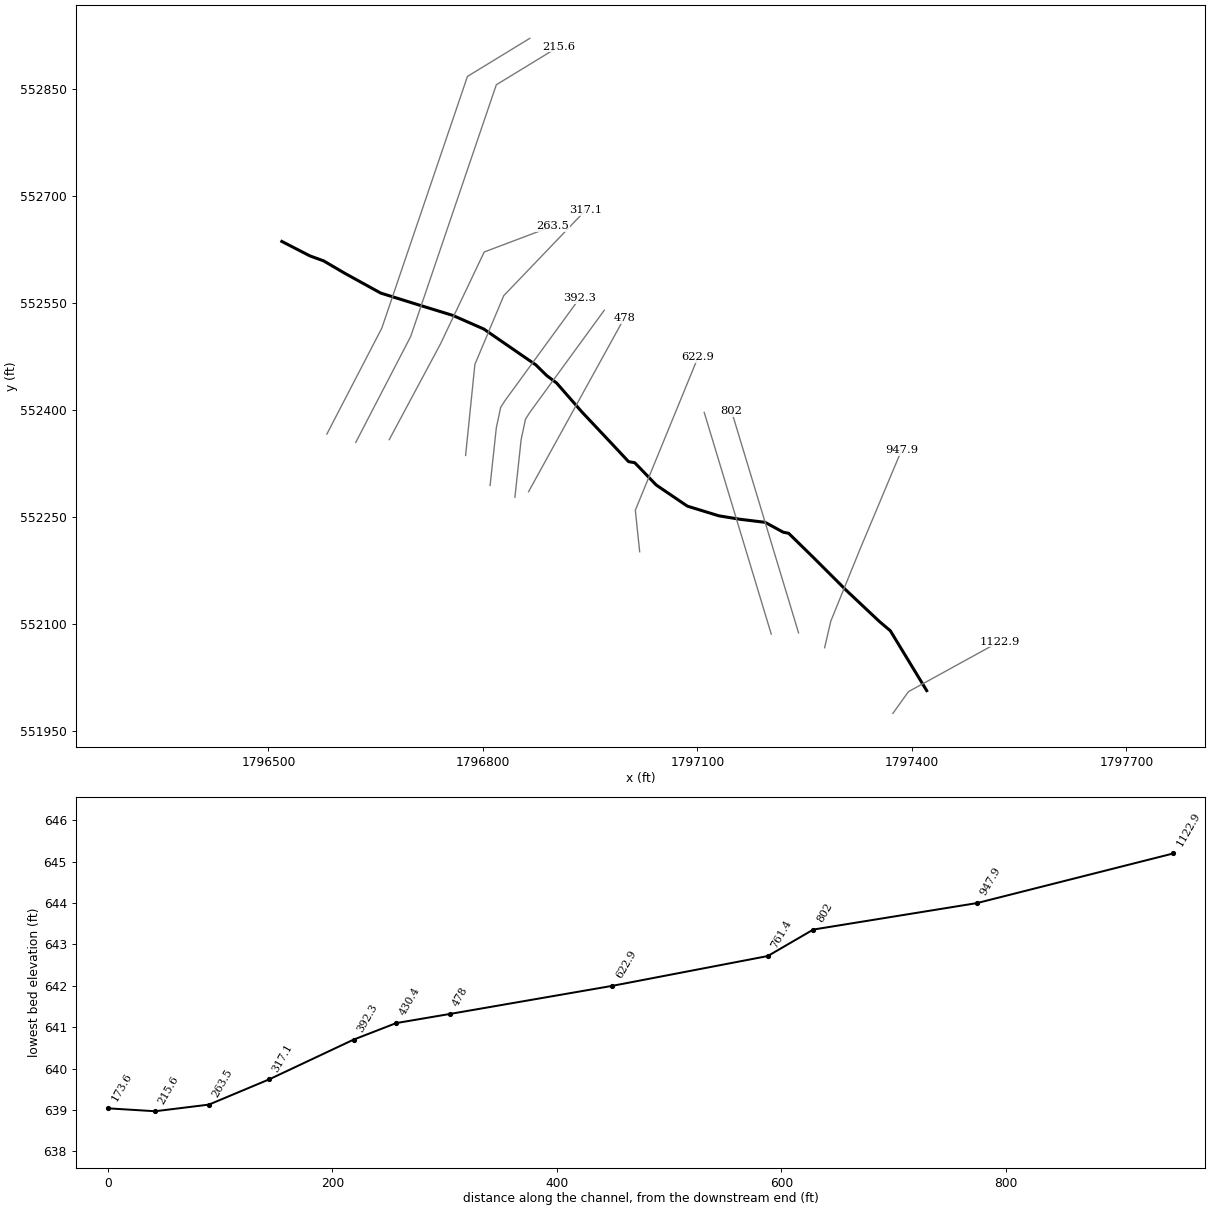
--- RFGRPVNCK.prj (project) ---

Proj Title=RFGRPVNCK
Current Plan=p01
Default Exp/Contr=0,0
English Units
Geom File=g01
Flow File=f01
Plan File=p01
BEGIN DESCRIPTION:
END DESCRIPTION:
DSS Export Rating Curves= 0
DSS Export Rating Curve Sorted= 0
DSS Export Volume Flow Curves= 0
DXF OffsetX= 0
DXF OffsetY= 0
DXF ScaleX= 0
DXF ScaleY= 0

--- RFGRPVNCK.p01 (plan) ---

Plan Title=Floodplain
Program Version=4.00
Geom File=g01
Flow File=f01
K Sum by GR=0
Std Step Tol=0.01
Critical Tol=0.01
Num of Std Step Trials=20
Max Error Tol=0.3
Flow Tol Ratio=0.001
Split Flow NTrial=30
Split Flow Tol=0.02
Split Flow Ratio=0.02
Log Output Level=0
Friction Slope Method=1
Unsteady Friction Slope Method=2
Unsteady Bridges Friction Slope Method=1
Global Log Level=0
CheckData=False
Run HTab=0
Run UNet=0
Run PostProcess=0
UNET Theta=0
UNET Theta Warmup=0
UNET ZTol=0
UNET ZSATol=0
UNET MxIter=0
UNET MaxInSteps=0
UNET DtIC=0
UNET DtMin=0
UNET MaxCRTS=0
UNET WFStab=0
UNET SFStab=0
UNET WFX=0
UNET SFX=0
UNET DSS MLevel=0
UNET DZMax Abort=0
UNET Convert EG Bridges=0
UNET Use Existing IB Tables=0
UNET Froude Limit=0
UNET Froude Power=0
Write IC File=0
Echo Input=False
Echo Output=False
Write Detailed=0

--- RFGRPVNCK.f01 (steady flow) ---

Flow Title=NFF Regression Equation
Program Version=4.10
Number of Profiles= 1
Profile Names=P100yr
River Rch & RM=RFGRPVNCK,Main            ,1122.9
868.4333
River Rch & RM=RFGRPVNCK,Main            ,478
 931.227
Boundary for River Rch & Prof#=RFGRPVNCK,Main            , 1
Up Type= 0
Dn Type= 3
Dn Slope=0.01
DSS Import GetInterval= 0
DSS Import GetPeak= 0
DSS Import FillOption= 0

--- RFGRPVNCK.g01 (geometry) ---

Geom Title=USGS 10m DEM
Program Version=4.10

River Reach=RFGRPVNCK       ,Main
Reach XY= 27
     1797420.714      552007.267      1797369.84      552091.207
     1797354.409      552104.301     1797308.402      552147.704
     1797259.791      552196.315     1797227.597      552227.823
     1797219.989      552229.345     1797194.686       552243.19
     1797159.096       552247.53     1797130.035      552252.307
     1797085.921      552265.881     1797042.519      552295.395
      1797012.39      552326.728     1797003.714      552328.259
     1796979.409      552354.301      1796938.61      552397.704
      1796903.02      552438.502     1796889.223        552448.9
     1796874.116      552463.797     1796801.199      552514.145
     1796757.796      552533.242     1796712.657      552547.131
     1796657.102      552564.492     1796606.755       552592.27
     1796577.241      552609.631     1796558.144      552616.575
     1796518.734       552636.91

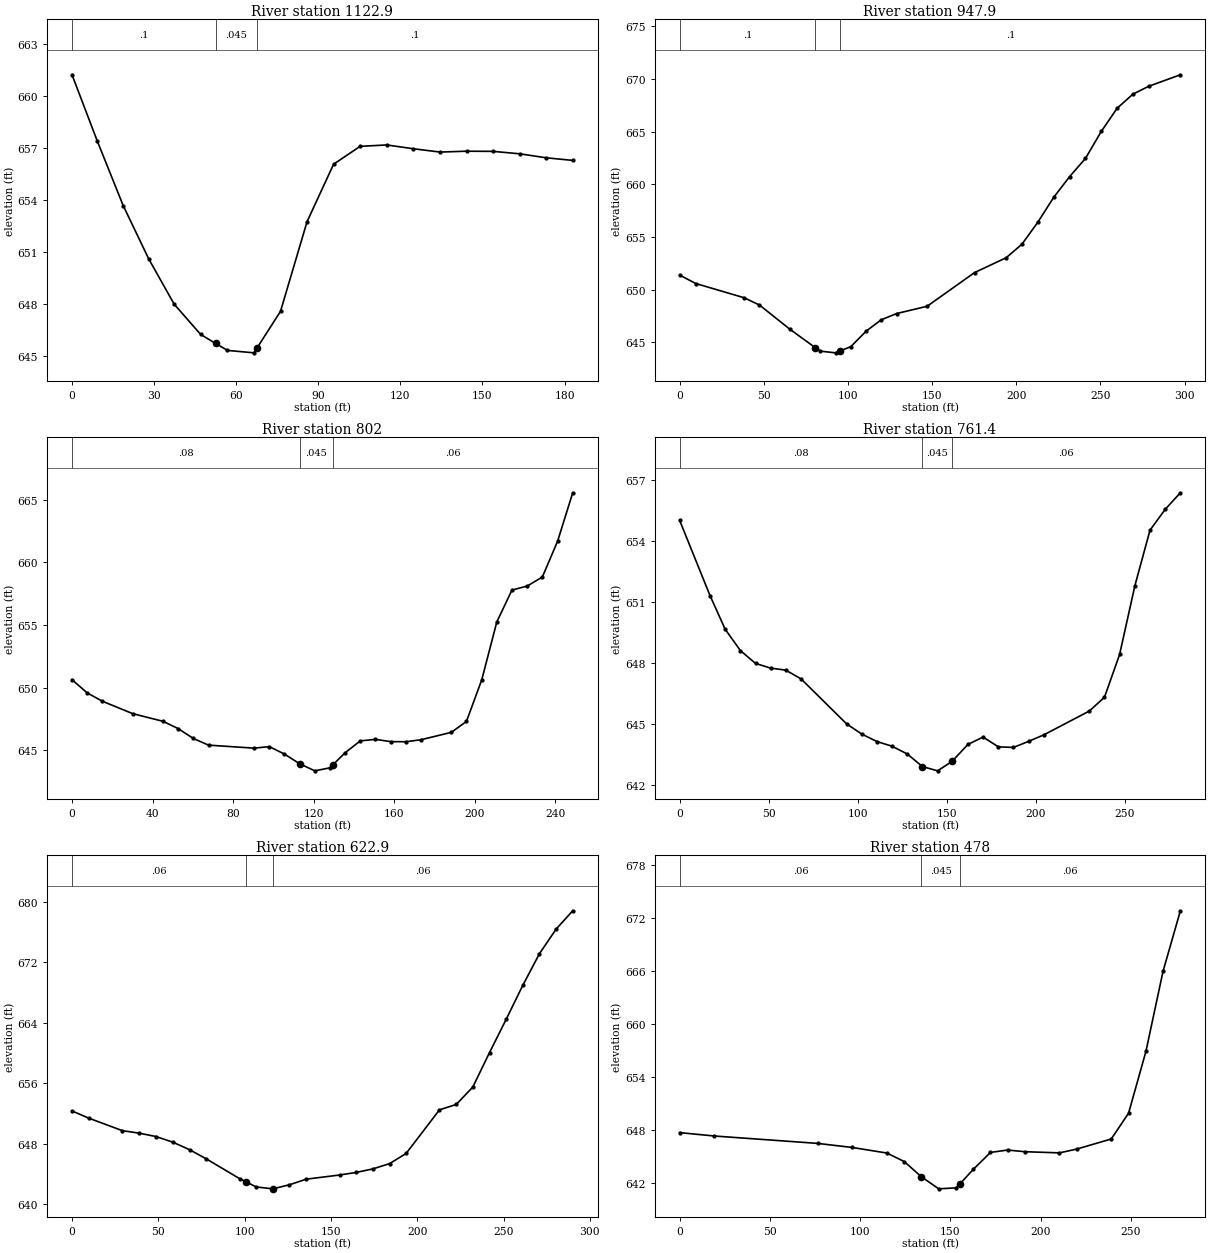
Type RM Length L Ch R = 1 ,1122.9  ,159.8,175,191.5
XS GIS Cut Line= 3
     1797373.419      551975.395      1797395.12      552005.777
     1797522.725      552076.089
#Sta/Elev= 22
       0  661.21     9.3  657.37    18.7  653.68      28  650.62    37.3  648.01
      47  646.26    52.5  645.74    56.8  645.34    66.5   645.2    67.5  645.45
    76.2  647.59    85.9  652.75    95.6  656.06   105.3  657.09     115  657.17
   124.8  656.95   134.5  656.76   144.2  656.81   153.9   656.8   163.6  656.66
   173.3  656.43     183  656.28
#Mann= 3 , 0 , 0
       0      .1       0    52.5    .045       0    67.5      .1       0
Bank Sta=52.5,67.5
XS Rating Curve= 0 ,0
Exp/Cntr=0.3,0.1

Type RM Length L Ch R = 1 ,947.9   ,126.4,145.9,160.5
XS GIS Cut Line= 4
     1797277.933      552067.409     1797286.614      552104.735
     1797327.412      552205.429     1797385.572      552344.318
#Sta/Elev= 26
       0  651.38     9.6  650.58    38.3  649.23    47.4  648.54    65.5  646.24
    80.5   644.5    83.6  644.16    92.6     644    95.5  644.19   101.7  644.59
   110.8  646.06   119.8  647.14   128.9  647.73     147  648.42   175.2  651.62
     194  653.03   203.4  654.32   212.8   656.4   222.3  658.78   231.7  660.73
   241.1  662.46   250.5  665.02   259.9  667.22   269.3  668.56   278.7  669.31
   297.5   670.4
#Mann= 3 , 0 , 0
       0      .1       0    80.5    .045       0    95.5      .1       0
Bank Sta=80.5,95.5
XS Rating Curve= 0 ,0
Exp/Cntr=0.3,0.1

Type RM Length L Ch R = 1 ,802     ,43.8,40.6,40.8
XS GIS Cut Line= 2
     1797241.475      552088.242     1797147.725      552399.006
#Sta/Elev= 30
       0  650.63   7.507  649.58  15.091  648.91  30.182  647.92  45.197  647.31
  52.704  646.73  60.288  645.94  67.795  645.41  90.393  645.17  97.977  645.29
 105.484   644.7 112.992  643.93 120.575  643.36 128.083   643.6 129.691  643.86
  135.59   644.8 143.174  645.75 150.681  645.87 158.265  645.69 165.772  645.68
 173.279  645.84  188.37  646.43 195.878   647.3 203.461  650.61 210.969  655.24
 218.476  657.78  226.06   658.1 233.567  658.82 241.151  661.68 248.658  665.54
#Mann= 3 , 0 , 0
       0     .08       0 112.992    .045       0 129.691     .06       0
Bank Sta=112.992,129.691
XS Rating Curve= 0 ,0
Skew Angle= 40
Exp/Cntr=0.3,0.1

Type RM Length L Ch R = 1 ,761.4   ,153.7,138.5,122.8
XS GIS Cut Line= 2
      1797203.28      552086.506      1797109.53       552397.27
#Sta/Elev= 29
       0  655.03  17.061  651.33  25.548  649.68  34.121  648.63  42.608     648
  51.095  647.77  59.583  647.67  68.156  647.24  93.704  645.03 102.191  644.53
 110.765  644.16 119.252  643.93 127.739  643.55 136.312  642.93 144.799  642.72
 152.853  643.18  161.86  644.02 170.347  644.38 178.921   643.9 187.408  643.87
 195.895  644.17 204.469  644.49 230.016  645.66 238.503  646.34  246.99  648.44
 255.564  651.82 264.051  654.55 272.625  655.58 281.112  656.39
#Mann= 3 , 0 , 0
       0     .08       0 136.312    .045       0 152.853     .06       0
Bank Sta=136.312,152.853
XS Rating Curve= 0 ,0
Skew Angle= 30
Exp/Cntr=0.3,0.1

Type RM Length L Ch R = 1 ,622.9   ,148.1,144.9,142.2
XS GIS Cut Line= 3
     1797019.252      552201.957     1797013.176      552260.117
      1797100.85      552474.527
#Sta/Elev= 28
       0  652.31     9.8  651.35    29.2   649.7      39  649.37    48.7  648.92
    58.5  648.17    68.1  647.18    77.8  645.97    97.1  643.35   100.8  642.93
   106.7  642.25   116.4     642     126  642.54   135.7  643.28     155  643.83
   164.6  644.17   174.3  644.64     184  645.34   193.6  646.69   212.9  652.46
   222.6  653.17   232.2  655.47   241.9  660.04   251.5  664.42   261.2  668.95
   270.8  673.12   280.5  676.39   290.1  678.81
#Mann= 3 , 0 , 0
       0     .06       0   100.8    .045       0   116.4     .06       0
Bank Sta=100.8,116.4
XS Rating Curve= 0 ,0
Exp/Cntr=0.3,0.1

Type RM Length L Ch R = 1 ,478     ,50.4,47.7,44.2
XS GIS Cut Line= 2
      1796863.87      552286.159     1796997.551      552529.214
#Sta/Elev= 21
       0  647.68    19.1   647.3    76.5  646.46    95.6     646   114.8  645.37
   124.4  644.41   133.9  642.69   143.5  641.32     153  641.43  155.45  641.92
   162.6  643.51   172.2  645.44   181.7  645.71   191.3  645.52   210.4  645.39
     220  645.82   239.1  646.96   248.7  649.88   258.3  656.86   267.8  665.94
   277.4  672.78
#Mann= 3 , 0 , 0
       0     .06       0   133.9    .045       0  155.45     .06       0
Bank Sta=133.9,155.45
XS Rating Curve= 0 ,0
Exp/Cntr=0.3,0.1

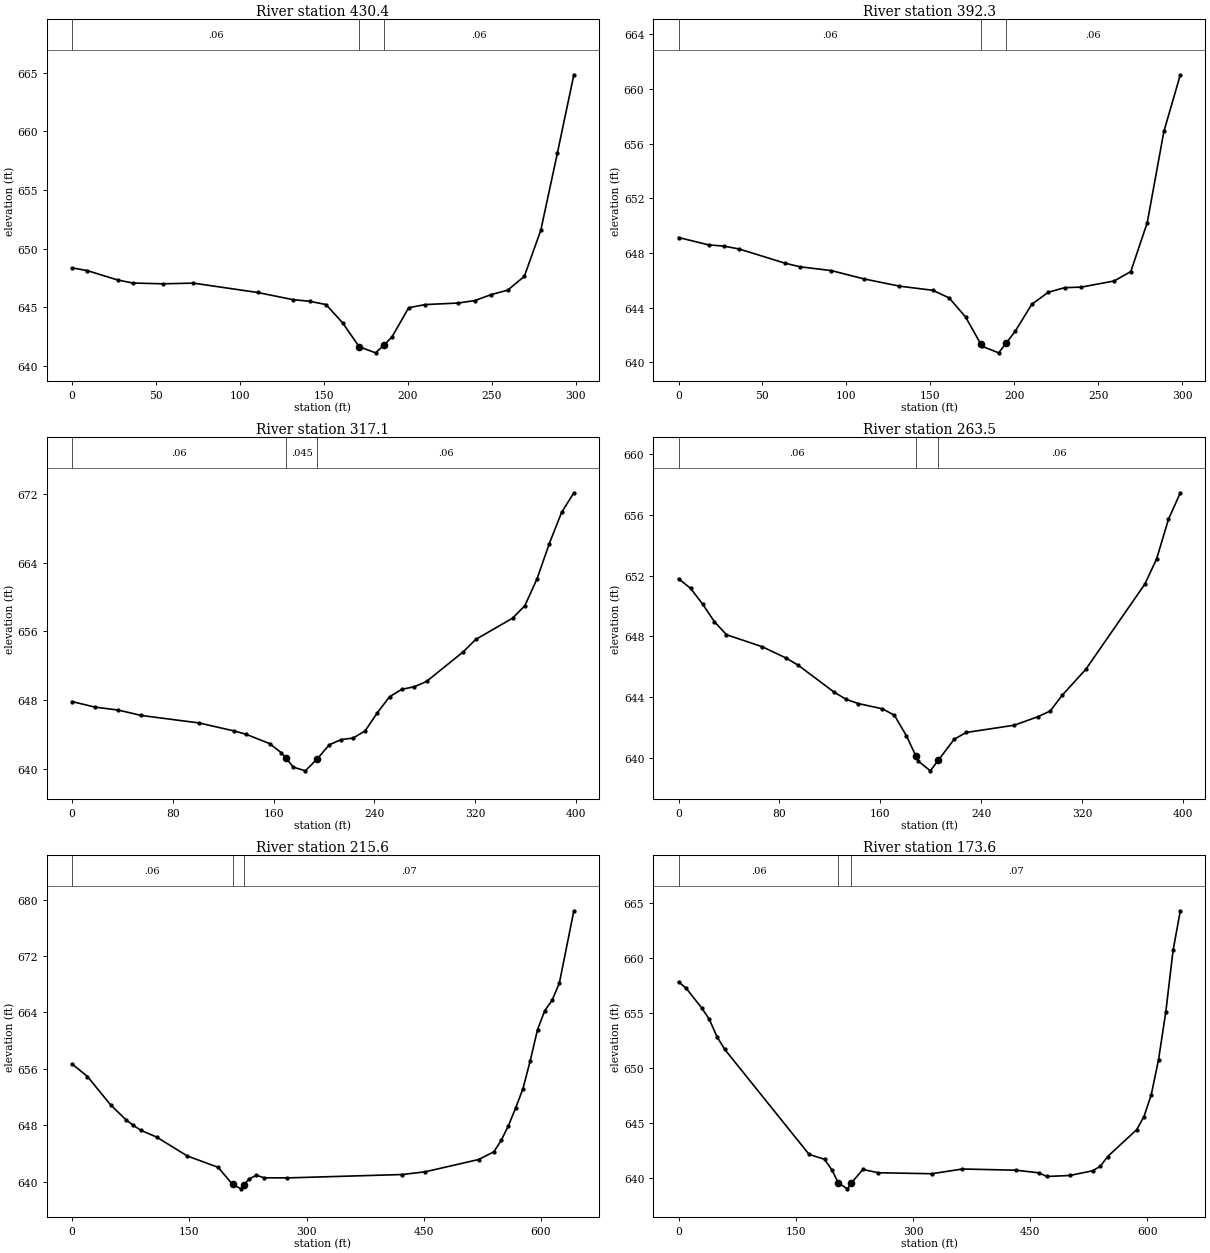
Type RM Length L Ch R = 1 ,430.4   ,37.9,38,37.9
XS GIS Cut Line= 5
     1796844.773      552278.346     1796853.454      552359.075
      1796859.53      552387.721     1796865.607       552397.27
     1796969.773      552540.499
#Sta/Elev= 25
       0  648.35       9  648.12    27.1  647.32    36.1  647.06    54.1  646.99
    72.2  647.05   110.5  646.25   131.6  645.64   141.5   645.5   151.3  645.22
   161.2  643.65     171  641.62   180.8   641.1  186.01  641.79   190.7  642.49
   200.5  644.95   210.4  645.22     230  645.35   239.9  645.56   249.7  646.07
   259.5  646.45   269.4  647.63   279.2  651.56   289.1  658.16   298.9  664.83
#Mann= 3 , 0 , 0
       0     .06       0     171    .045       0  186.01     .06       0
Bank Sta=171,186.01
XS Rating Curve= 0 ,0
Exp/Cntr=0.3,0.1

Type RM Length L Ch R = 1 ,392.3   ,69.9,75.2,80.5
XS GIS Cut Line= 5
     1796810.051      552294.839     1796818.732      552375.568
     1796824.808      552404.214     1796830.884      552413.763
     1796935.051      552556.992
#Sta/Elev= 26
       0  649.14      18   648.6    27.1  648.51    36.1   648.3    63.2  647.27
    72.2     647      91  646.72   110.5  646.11   131.6  645.58   151.3  645.28
   161.2  644.72     171  643.32   180.1  641.33   180.8  641.18   190.7   640.7
   195.1   641.4   200.5  642.27   210.4  644.25   220.2  645.13     230  645.47
   239.9  645.51   259.5  645.96   269.4  646.65   279.2  650.23   289.1   656.9
   298.9  661.05
#Mann= 3 , 0 , 0
       0     .06       0   180.1    .045       0   195.1     .06       0
Bank Sta=180.1,195.1
XS Rating Curve= 0 ,0
Exp/Cntr=0.3,0.1

Type RM Length L Ch R = 1 ,317.1   ,54.8,53.7,52.5
XS GIS Cut Line= 4
     1796775.763       552336.94     1796788.784      552464.544
     1796829.148      552560.898     1796943.732       552680.69
#Sta/Elev= 30
       0  647.81    18.3  647.16    36.6  646.82      55  646.19   100.8  645.32
   128.3   644.4   137.8  644.02   156.8  642.92   166.2  641.85   169.7  641.24
   175.8  640.17   185.2  639.74   194.8  641.14   204.2  642.77   213.7  643.38
   223.2  643.56   232.7  644.39   242.5  646.52   252.2  648.38     262  649.24
   271.7  649.53   281.5  650.15   310.7  653.61   320.5  655.04   349.8  657.52
   359.5  658.96   369.2  662.08     379  666.21   388.8  669.85   398.5  672.13
#Mann= 3 , 0 , 0
       0     .06       0   169.7    .045       0   194.8     .06       0
Bank Sta=169.7,194.8
XS Rating Curve= 0 ,0
Exp/Cntr=0.3,0.1

Type RM Length L Ch R = 1 ,263.5   ,45.3,47.9,50.5
XS GIS Cut Line= 4
     1796668.992      552359.075     1796740.607       552493.19
     1796801.804      552622.096     1796898.159      552658.554
#Sta/Elev= 29
       0   651.8     9.5  651.17      19  650.14    28.5  648.96      38  648.11
    66.5  647.31    85.5  646.56      95  646.09   123.5  644.31     133  643.84
   142.5  643.57   161.6  643.22   171.1   642.8   180.6  641.45   188.1  640.12
   190.1  639.77   199.6  639.13  205.85  639.82   218.6  641.22   228.1  641.66
   266.2  642.14   285.2  642.71   294.7  643.08   304.1  644.11   322.8  645.82
   369.7  651.45     379  653.11   388.4  655.72   397.8  657.47
#Mann= 3 , 0 , 0
       0     .06       0   188.1    .045       0  205.85     .06       0
Bank Sta=188.1,205.85
XS Rating Curve= 0 ,0
Exp/Cntr=0.3,0.1

Type RM Length L Ch R = 1 ,215.6   ,42,42,42
XS GIS Cut Line= 4
     1796622.117      552355.169      1796698.94      552503.607
     1796818.732      552856.471     1796905.971      552909.857
#Sta/Elev= 30
       0   656.7    19.7  654.91    49.2   650.9    68.8  648.79    78.6  647.96
    88.5  647.25   108.2  646.32   147.5  643.63   186.8  642.03   205.3  639.61
   216.2  638.97   220.3  639.54     226  640.34   235.8   640.9   245.6  640.54
     275  640.52   422.1     641   451.5  641.38   520.2  643.13   539.8  644.23
   549.1  645.84   558.4  647.94   567.7  650.47     577  653.19   586.3  657.17
   595.6  661.56   604.9  664.26   614.2  665.72   623.5  668.16   642.1  678.43
#Mann= 3 , 0 , 0
       0     .06       0   205.3    .045       0   220.3     .07       0
Bank Sta=205.3,220.3
XS Rating Curve= 0 ,0
Exp/Cntr=0.3,0.1

Type RM Length L Ch R = 1 ,173.6   ,176,173.6,171
XS GIS Cut Line= 4
     1796581.752      552366.888     1796658.575      552515.325
     1796778.367       552868.19     1796865.607      552921.575
#Sta/Elev= 30
       0  657.82     9.8  657.23    29.5  655.46    39.3  654.42    49.2  652.84
      59   651.7   167.1  642.16   186.8  641.72   196.6  640.72  204.44  639.57
   216.2  639.04   221.1  639.56   235.8   640.8   255.4   640.5     324  640.41
   363.3  640.84   431.9  640.73   461.3  640.49   471.1  640.16   500.6  640.25
     530  640.68   539.8  641.09   549.1  641.97   586.3  644.41   595.6   645.6
   604.9  647.58   614.2  650.75   623.5  655.08   632.8  660.66   642.1  664.26
#Mann= 3 , 0 , 0
       0     .06       0  204.44    .045       0   221.1     .07       0
Bank Sta=204.44,221.1
XS Rating Curve= 0 ,0
Exp/Cntr=0.3,0.1

Chan Stop Cuts=-1
Use User Specified Reach Order=0
Composite Channel Slope=5